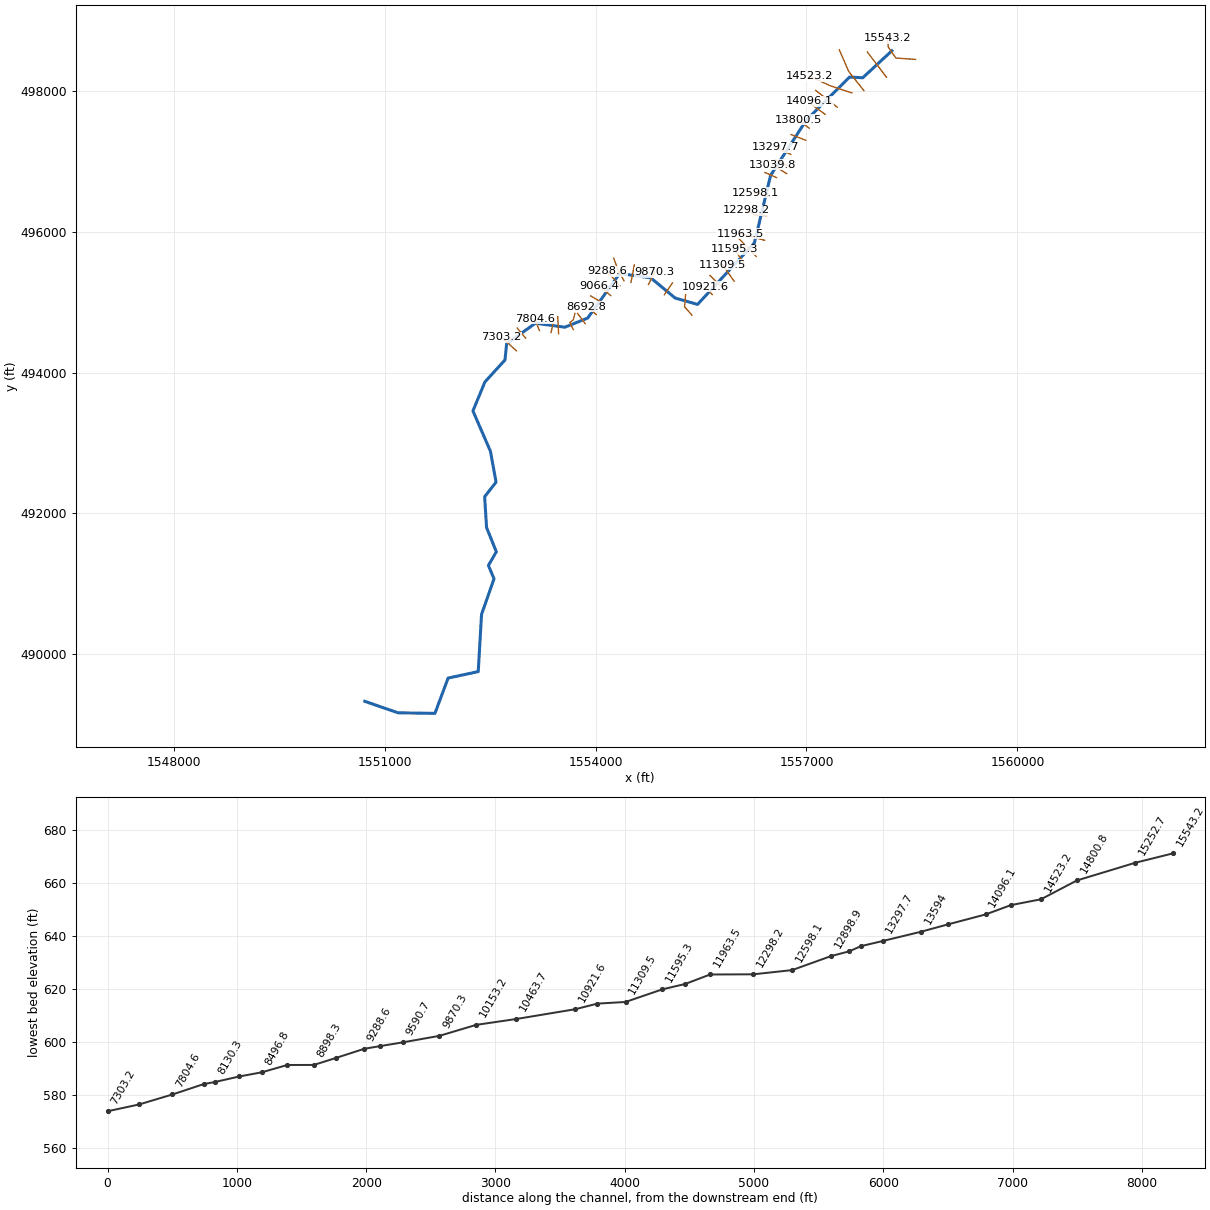
--- NRTHCMPCR.prj (project) ---

Proj Title=NRTHCMPCR
Current Plan=p01
Default Exp/Contr=0,0
English Units
Geom File=g01
Flow File=f01
Plan File=p01
BEGIN DESCRIPTION:
END DESCRIPTION:
DSS Export Rating Curves= 0
DSS Export Rating Curve Sorted= 0
DSS Export Volume Flow Curves= 0
DXF OffsetX= 0
DXF OffsetY= 0
DXF ScaleX= 0
DXF ScaleY= 0

--- NRTHCMPCR.p01 (plan) ---

Plan Title=Floodplain
Program Version=4.00
Geom File=g01
Flow File=f01
K Sum by GR=0
Std Step Tol=0.01
Critical Tol=0.01
Num of Std Step Trials=20
Max Error Tol=0.3
Flow Tol Ratio=0.001
Split Flow NTrial=30
Split Flow Tol=0.02
Split Flow Ratio=0.02
Log Output Level=0
Friction Slope Method=1
Unsteady Friction Slope Method=2
Unsteady Bridges Friction Slope Method=1
Global Log Level=0
CheckData=False
Run HTab=0
Run UNet=0
Run PostProcess=0
UNET Theta=0
UNET Theta Warmup=0
UNET ZTol=0
UNET ZSATol=0
UNET MxIter=0
UNET MaxInSteps=0
UNET DtIC=0
UNET DtMin=0
UNET MaxCRTS=0
UNET WFStab=0
UNET SFStab=0
UNET WFX=0
UNET SFX=0
UNET DSS MLevel=0
UNET DZMax Abort=0
UNET Convert EG Bridges=0
UNET Use Existing IB Tables=0
UNET Froude Limit=0
UNET Froude Power=0
Write IC File=0
Echo Input=False
Echo Output=False
Write Detailed=0

--- NRTHCMPCR.f01 (steady flow) ---

Flow Title=NFF Regression Equation
Program Version=4.00
Number of Profiles=1
Profile Names=P100yr
River Rch & RM=NRTHCMPCR,Main      ,15543.2
357.6627
River Rch & RM=NRTHCMPCR,Main      ,13800.5
378.7352
River Rch & RM=NRTHCMPCR,Main      ,12898.9
407.0928
River Rch & RM=NRTHCMPCR,Main      ,12598.1
459.5068
River Rch & RM=NRTHCMPCR,Main      ,12298.2
461.9521
River Rch & RM=NRTHCMPCR,Main      ,9590.7
512.3671
River Rch & RM=NRTHCMPCR,Main      ,9288.6
570.3230
River Rch & RM=NRTHCMPCR,Main      ,6592.4
608.6330
River Rch & RM=NRTHCMPCR,Main      ,6292.3
783.6058
Boundary for River Rch & Prof#=NRTHCMPCR,Main      ,1
Up Type=0
Dn Type=3
Dn Slope=0.005288

--- NRTHCMPCR.g01 (geometry) ---

Geom Title=Geometry
Program Version=4.00

River Reach=NRTHCMPCR       ,Main
Reach XY= 30
     1558215.575      498574.367     1557800.419      498190.499
     1557612.959      498200.508     1556997.254      497586.866
     1556489.986      496803.039     1556259.706      495842.384
     1555451.519      494969.528      1555133.63      495059.703
     1554785.971      495346.816     1554343.605      495408.594
     1553889.256      494776.199     1553564.556      494645.543
     1553145.897      494702.025     1552735.944      494411.407
     1552712.558      494179.707     1552427.369      493867.971
      1552256.63      493456.376     1552505.616      492883.166
     1552585.716      492443.422     1552423.071      492235.942
     1552450.642      491797.876     1552589.713      491454.407
     1552476.983        491259.7     1552556.678      491070.223
     1552379.145      490563.507     1552332.185      489750.943
      1551903.62      489658.871     1551715.904      489157.325
     1551191.853      489165.303     1550718.429      489328.611

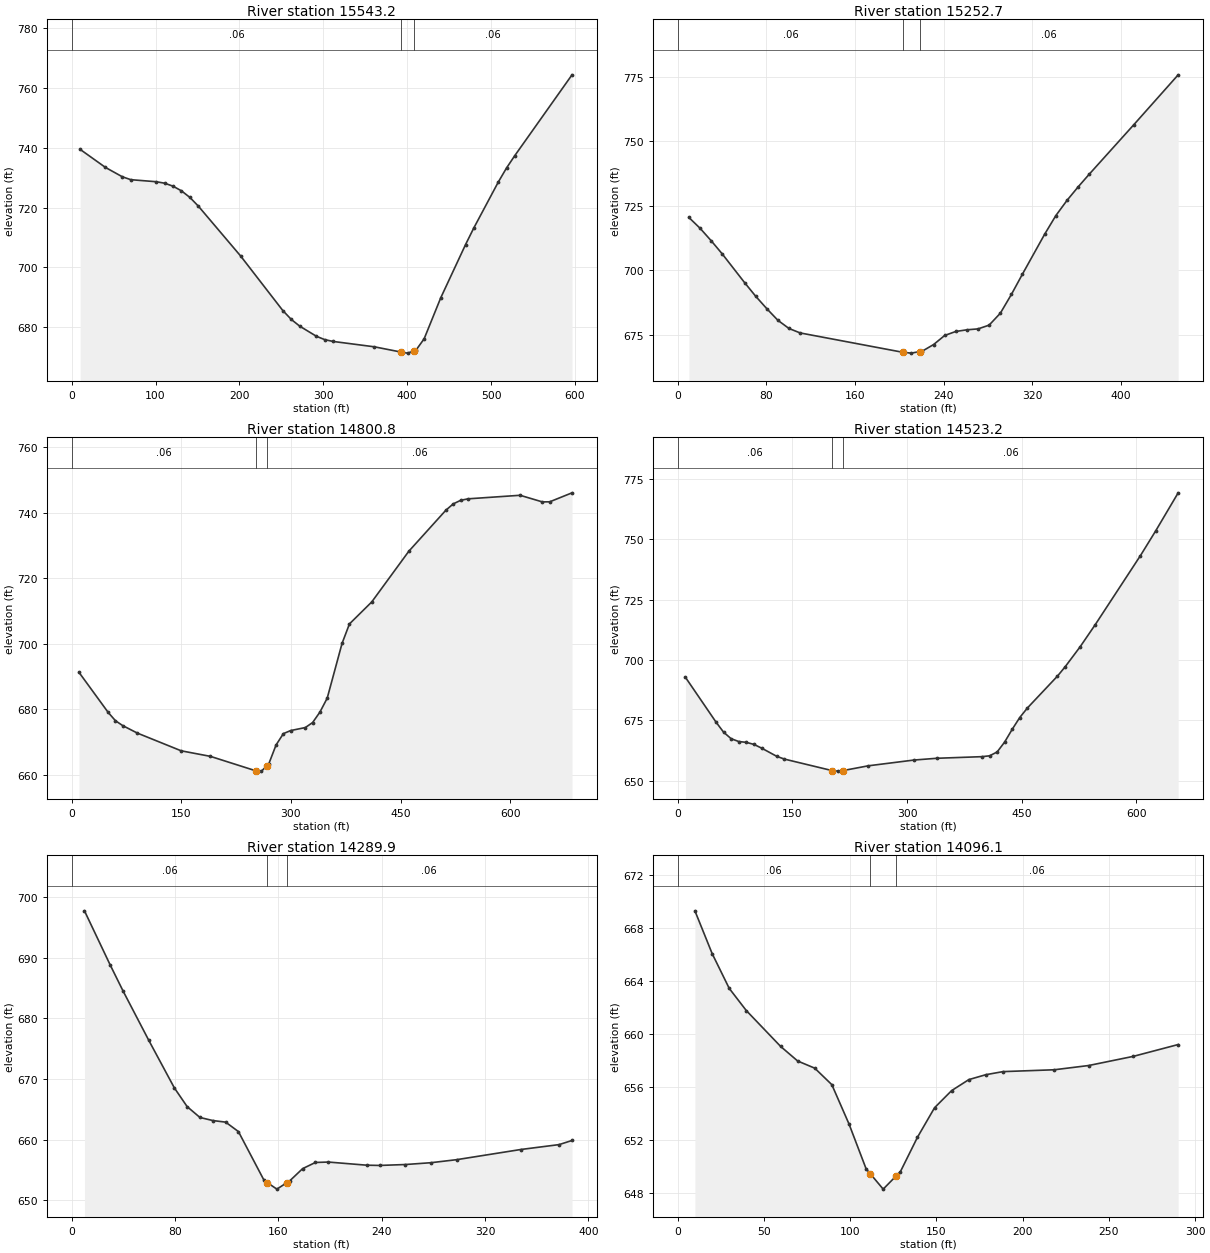
Type RM Length L Ch R = 1 ,15543.2 ,287.9,290.6,293.3
XS GIS Cut Line= 4
     1558553.751      498451.183     1558272.519      498470.998
     1558165.069      498624.847     1558150.556       498750.92
#Sta/Elev= 30
    10.1  739.46    40.3  733.42    60.4   730.3    70.5  729.33   100.7  728.65
   110.8  728.16   120.8  727.16   130.9   725.6     141  723.38     151  720.49
   201.4  703.82   251.7  685.58   261.8  682.61   271.9  680.35   291.8  676.97
   301.7  675.85   311.6  675.25   360.9  673.45   392.9  671.68   400.4  671.34
   407.9  672.05   410.3  672.27   420.2  676.13     440  689.84   469.6  707.65
   479.3  713.13   508.6  728.54   518.4  733.23   528.2  737.35   596.5  764.39
#Mann= 3 , 0 , 0
       0     .06       0   392.9    .045       0   407.9     .06       0
Bank Sta=392.9,407.9
XS Rating Curve= 0 ,0
Exp/Cntr=0.3,0.1

Type RM Length L Ch R = 1 ,15252.7 ,450.5,451.8,447
XS GIS Cut Line= 2
     1558138.975      498197.668     1557865.707      498557.074
#Sta/Elev= 30
      10  720.42    20.1  716.23    30.1   711.4    40.1  706.28    60.2  695.18
    70.2   689.9    80.3  685.04    90.3  680.54   100.3  677.37   110.4  675.64
   203.2  668.12   210.7  667.81   218.2  668.41   220.7  668.61   230.8  671.14
   240.8  674.66   250.8  676.21   260.9  676.86   270.9  677.21   280.9  678.67
     291  683.28     301  690.58     311  698.48   331.1     714   341.1  721.15
   351.2  727.07   361.2  732.28   371.2  737.19   411.4  756.38   451.5  775.76
#Mann= 3 , 0 , 0
       0     .06       0   203.2    .045       0   218.2     .06       0
Bank Sta=203.2,218.2
XS Rating Curve= 0 ,0
Exp/Cntr=0.3,0.1

Type RM Length L Ch R = 1 ,14800.8 ,264,277.6,291.1
XS GIS Cut Line= 3
     1557818.183      498007.569     1557600.648       498281.32
     1557467.386      498588.679
#Sta/Elev= 30
      10  691.28      50  679.03    59.9  676.51    69.9  675.01    89.9  672.73
   149.9  667.32   189.8  665.63   252.2   661.2   259.7  661.12   267.2  662.77
   269.7  663.32   279.7  669.11   289.7  672.57   299.7  673.51   319.7  674.42
   329.7  675.95   339.7  679.14   349.7  683.41     370  700.12   380.1  706.06
   410.6  712.77   461.3  728.24   512.1  740.79   522.2  742.72   532.4  743.81
   542.5  744.26   613.6  745.34   644.1  743.32   654.2  743.35   684.7  746.09
#Mann= 3 , 0 , 0
       0     .06       0   252.2    .045       0   267.2     .06       0
Bank Sta=252.2,267.2
XS Rating Curve= 0 ,0
Exp/Cntr=0.3,0.1

Type RM Length L Ch R = 1 ,14523.2 ,242.5,233.3,224
XS GIS Cut Line= 3
     1557645.905      497974.895     1557333.963      498078.876
     1557038.705      498216.651
#Sta/Elev= 30
      10  692.85    49.8  674.39    59.8  670.17    69.7  667.45    79.7  666.28
    89.7  665.93    99.6  665.08   109.6  663.55   129.5  660.13   139.5     659
   201.7  654.25   209.2  654.02   216.7  654.28   249.1  656.22   308.9  658.61
   338.7  659.34   397.9  660.01   407.8  660.36   417.7  661.94   427.5  666.03
   437.4  671.31   447.3   676.2   457.2  680.12   496.7  693.38   506.5  697.14
   526.3   705.5     546  714.63   605.3  743.31     625  753.42   654.6  769.27
#Mann= 3 , 0 , 0
       0     .06       0   201.7    .045       0   216.7     .06       0
Bank Sta=201.7,216.7
XS Rating Curve= 0 ,0
Exp/Cntr=0.3,0.1

Type RM Length L Ch R = 1 ,14289.9 ,192.9,193.8,194.7
XS GIS Cut Line= 2
     1557437.984      497772.915     1557132.043      498010.539
#Sta/Elev= 26
     9.9  697.75    29.8  688.82    39.7  684.55    59.6  676.41    79.5  668.52
    89.4  665.43    99.3  663.64   109.3  663.13   119.2  662.87   129.1  661.31
     149  653.24   151.4  652.89   158.9  651.81   166.4  652.85   168.9  653.19
   178.8  655.19   188.7  656.21   198.7  656.28   228.5  655.76   238.4  655.72
   258.3  655.87   278.1  656.17     298  656.67   347.7  658.35   377.4  659.16
   387.4  659.84
#Mann= 3 , 0 , 0
       0     .06       0   151.4    .045       0   166.4     .06       0
Bank Sta=151.4,166.4
XS Rating Curve= 0 ,0
Exp/Cntr=0.3,0.1

Type RM Length L Ch R = 1 ,14096.1 ,296.3,295.6,295
XS GIS Cut Line= 3
     1557265.389      497671.186      1557072.32       497810.79
     1557045.587      497855.344
#Sta/Elev= 24
     9.9  669.27    19.9  666.05    29.8  663.43    39.7  661.76    59.6  659.06
    69.5  657.96    79.4  657.42    89.3  656.18    99.3  653.21   109.2  649.84
   111.6  649.47   119.1  648.31   126.6   649.3   129.1  649.63     139  652.22
   148.9  654.44   158.8  655.73   168.8  656.56   178.7  656.93   188.6  657.16
   218.4   657.3   238.3  657.62   264.2  658.31   290.2   659.2
#Mann= 3 , 0 , 0
       0     .06       0   111.6    .045       0   126.6     .06       0
Bank Sta=111.6,126.6
XS Rating Curve= 0 ,0
Exp/Cntr=0.3,0.1

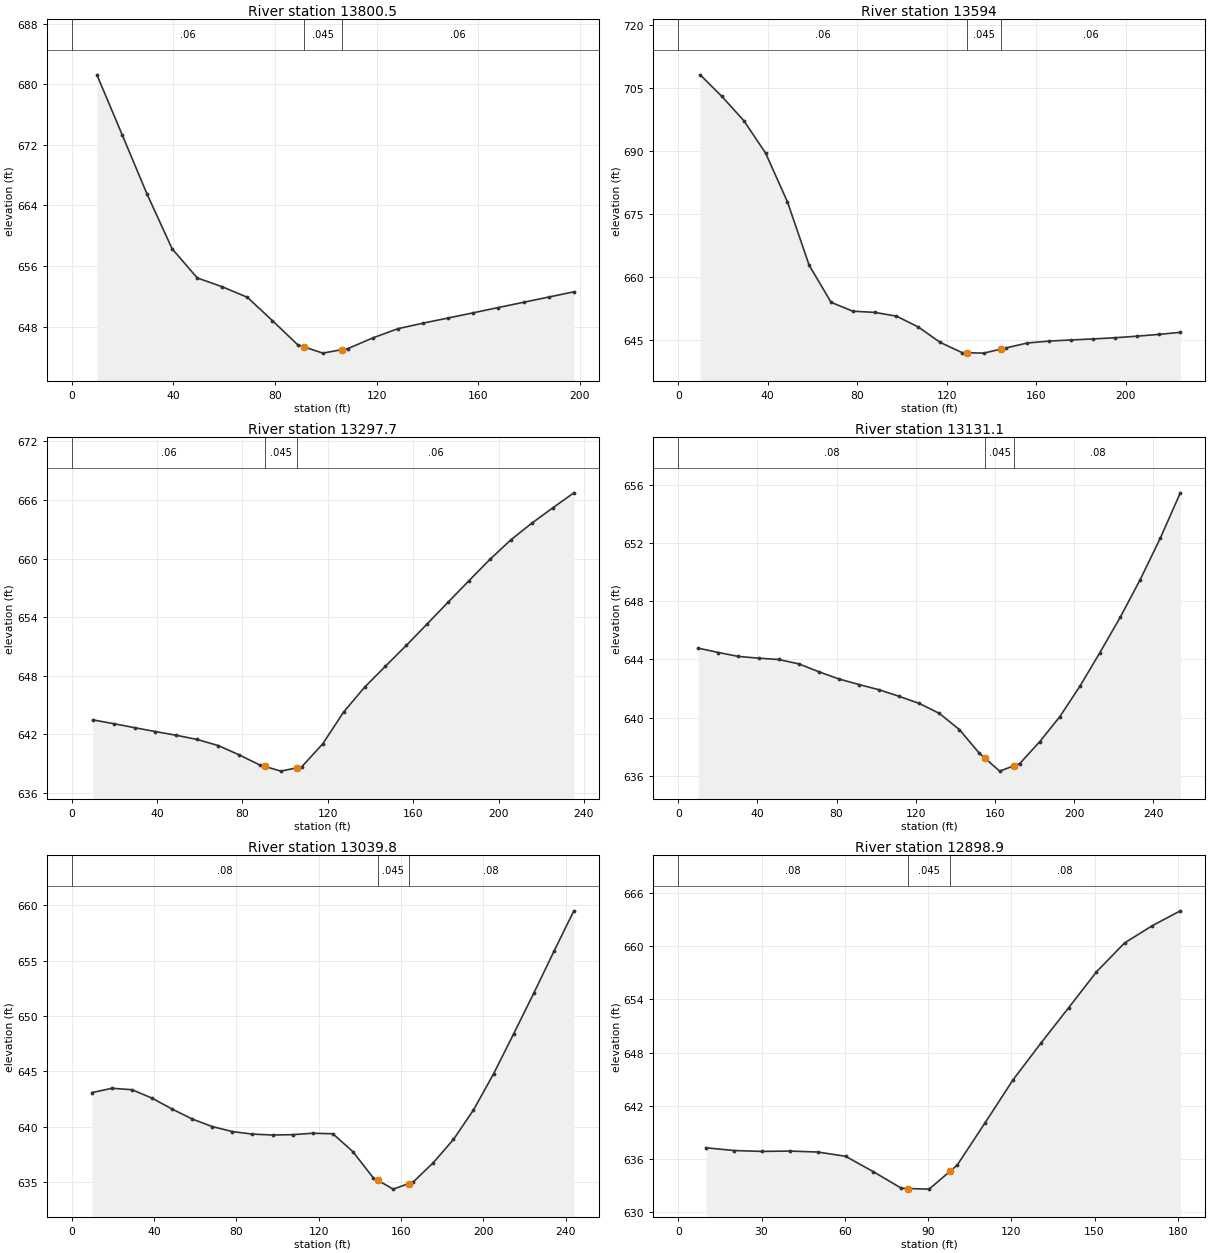
Type RM Length L Ch R = 1 ,13800.5 ,200.2,206.5,212.8
XS GIS Cut Line= 2
     1557038.778      497474.731     1556881.253      497593.947
#Sta/Elev= 22
     9.9  681.23    19.8  673.35    29.6  665.51    39.5  658.27    49.4  654.42
    59.3  653.25    69.1  651.87      79  648.78    88.9  645.61    91.3  645.34
    98.8   644.5   106.3  644.96   108.7   645.1   118.5  646.51   128.4  647.73
   138.3  648.46   148.2  649.14     158  649.82   167.9  650.52   177.8  651.21
   187.7   651.9   197.6  652.59
#Mann= 3 , 0 , 0
       0     .06       0    91.3    .045       0   106.3     .06       0
Bank Sta=91.3,106.3
XS Rating Curve= 0 ,0
Exp/Cntr=0.3,0.1

Type RM Length L Ch R = 1 ,13594   ,298,296.3,294.6
XS GIS Cut Line= 2
     1556990.505      497302.243     1556781.548      497383.806
#Sta/Elev= 25
     9.8   708.2    19.5  703.04    29.3  697.26      39  689.54    48.8  677.86
    58.5  662.72    68.3  653.88      78  651.76    87.8  651.48    97.5  650.58
   107.3  647.98     117  644.32   126.8  641.87     129  641.85   136.5  641.75
     144  642.69   146.3  642.98     156  644.17   165.8  644.63   175.5  644.89
   185.3  645.14   195.1  645.42   204.8  645.79   214.6  646.22   224.3  646.72
#Mann= 3 , 0 , 0
       0     .06       0     129    .045       0     144     .06       0
Bank Sta=129,144
XS Rating Curve= 0 ,0
Exp/Cntr=0.3,0.1

Type RM Length L Ch R = 1 ,13297.7 ,167,166.5,166.1
XS GIS Cut Line= 2
     1556778.577      497101.627     1556564.716      497199.647
#Sta/Elev= 26
     9.8   643.5    19.6  643.11    29.4   642.7    39.2   642.3      49  641.92
    58.8  641.49    68.6  640.87    78.4  639.92    88.2  638.87    90.5  638.73
      98  638.25   105.5  638.59   107.8   638.7   117.6  641.04   127.4   644.3
   137.2  646.83     147  648.99   156.8  651.12   166.6  653.33   176.4  655.55
   186.2  657.76     196  659.93   205.8  661.93   215.7  663.65   225.5  665.21
   235.3  666.74
#Mann= 3 , 0 , 0
       0     .06       0    90.5    .045       0   105.5     .06       0
Bank Sta=90.5,105.5
XS Rating Curve= 0 ,0
Exp/Cntr=0.3,0.1

Type RM Length L Ch R = 1 ,13131.1 ,93.7,91.3,88.9
XS GIS Cut Line= 2
     1556784.518      496914.498     1556555.805      497024.399
#Sta/Elev= 27
    10.1  644.78    20.3  644.48    30.4  644.21    40.6  644.09    50.7     644
    60.9   643.7      71  643.16    81.2  642.66    91.3  642.28   101.5  641.92
   111.6  641.47   121.8  640.98   131.9   640.3   142.1  639.18   152.2  637.55
   154.9  637.23   162.4  636.33   169.9  636.71   172.5  636.84   182.7  638.36
   192.8  640.07     203  642.17   213.1  644.48   223.3  646.89   233.4  649.48
   243.6  652.34   253.7  655.45
#Mann= 3 , 0 , 0
       0     .08       0   154.9    .045       0   169.9     .08       0
Bank Sta=154.9,169.9
XS Rating Curve= 0 ,0
Exp/Cntr=0.3,0.1

Type RM Length L Ch R = 1 ,13039.8 ,137.6,140.9,144.2
XS GIS Cut Line= 2
     1556719.171      496828.359      1556511.25      496956.082
#Sta/Elev= 27
     9.8  643.09    19.5  643.48    29.3  643.35      39  642.59    48.8   641.6
    58.6   640.7    68.3  640.02    78.1  639.57    87.8  639.34    97.6  639.26
   107.4  639.29   117.1  639.42   126.9  639.37   136.6  637.76   146.4  635.42
   148.7  635.17   156.2  634.37   163.7  634.87   165.9  635.01   175.7  636.76
   185.5  638.86   195.2  641.51     205  644.79   214.7  648.38   224.5  652.06
   234.3  655.84     244  659.51
#Mann= 3 , 0 , 0
       0     .08       0   148.7    .045       0   163.7     .08       0
Bank Sta=148.7,163.7
XS Rating Curve= 0 ,0
Exp/Cntr=0.3,0.1

Type RM Length L Ch R = 1 ,12898.9 ,296.9,300.8,304.8
XS GIS Cut Line= 2
     1556576.137      496771.314     1556410.567      496844.165
#Sta/Elev= 20
      10  637.24    20.1  636.93    30.1  636.83    40.2  636.87    50.2  636.76
    60.3  636.28    70.3  634.54    80.4  632.67    82.9  632.64    90.4  632.57
    97.9  634.58   100.5  635.28   110.5  640.03   120.6   644.9   130.6  649.03
   140.7  653.07   150.7  657.11   160.8  660.37   170.8  662.32   180.9     664
#Mann= 3 , 0 , 0
       0     .08       0    82.9    .045       0    97.9     .08       0
Bank Sta=82.9,97.9
XS Rating Curve= 0 ,0
Exp/Cntr=0.3,0.1

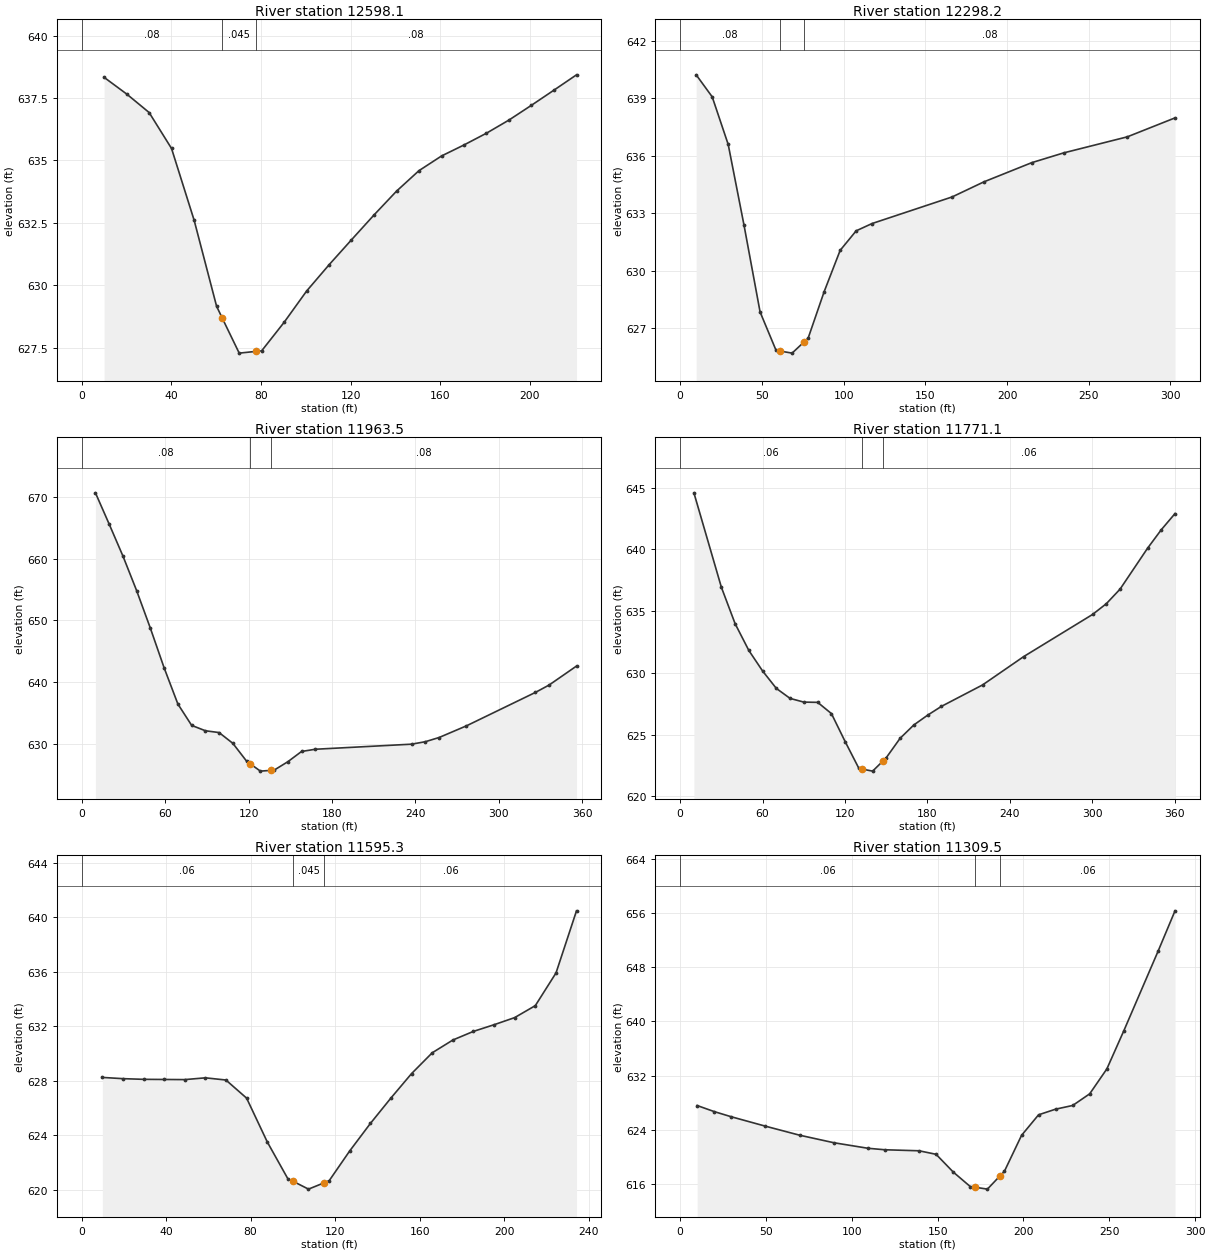
Type RM Length L Ch R = 1 ,12598.1 ,295.2,299.9,303.9
XS GIS Cut Line= 2
     1556485.626      496503.457     1556270.752      496554.232
#Sta/Elev= 24
      10  638.33    20.1  637.66    30.1  636.92    40.1  635.48    50.2   632.6
    60.2  629.16    62.8  628.67    70.3  627.28    77.8  627.35    80.3  627.37
    90.3  628.51   100.4  629.77   110.4  630.82   120.4  631.82   130.5  632.82
   140.5  633.77   150.5  634.59   160.6  635.18   170.6  635.62   180.6  636.09
   190.7  636.62   200.7  637.21   210.8  637.82   220.8  638.43
#Mann= 3 , 0 , 0
       0     .08       0    62.8    .045       0    77.8     .08       0
Bank Sta=62.8,77.8
XS Rating Curve= 0 ,0
Exp/Cntr=0.3,0.1

Type RM Length L Ch R = 1 ,12298.2 ,339.8,334.7,330.3
XS GIS Cut Line= 3
     1556434.758      496231.904     1556268.544       496239.28
      1556149.61      496306.161
#Sta/Elev= 20
     9.8  640.23    19.6  639.08    29.4  636.59    39.1  632.36    48.9  627.84
    58.7  625.83      61   625.8    68.5  625.69      76  626.29    78.3  626.47
    88.1   628.9    97.9  631.06   107.7  632.08   117.4  632.46   166.4  633.85
   185.9  634.64   215.1  635.64   234.6  636.15   273.6  636.99   302.8  637.98
#Mann= 3 , 0 , 0
       0     .08       0      61    .045       0      76     .08       0
Bank Sta=61,76
XS Rating Curve= 0 ,0
Exp/Cntr=0.3,0.1

Type RM Length L Ch R = 1 ,11963.5 ,204.3,192.4,180.4
XS GIS Cut Line= 2
     1556406.044      495880.258     1556063.168      495975.356
#Sta/Elev= 26
     9.9  670.65    19.8  665.58    29.7  660.41    39.5  654.84    49.4  648.75
    59.3  642.33    69.2  636.47    79.1  633.02      89  632.15    98.8  631.86
   108.7  630.12   118.6  627.23     121  626.84   128.5  625.62     136  625.74
   138.4  625.78   148.3  627.15   158.1   628.8     168  629.16   237.2  629.98
   247.1  630.38     257  631.06   276.7  632.95   326.2  638.35   336.1  639.55
   355.8  642.62
#Mann= 3 , 0 , 0
       0     .08       0     121    .045       0     136     .08       0
Bank Sta=121,136
XS Rating Curve= 0 ,0
Exp/Cntr=0.3,0.1

Type RM Length L Ch R = 1 ,11771.1 ,179,175.9,172.7
XS GIS Cut Line= 2
     1556286.228      495651.114     1556034.423      495908.668
#Sta/Elev= 28
      10  644.58      30  636.93      40  633.98      50  631.81      60  630.15
      70  628.74      80  627.93      90  627.63   100.1  627.61   110.1   626.7
   120.1  624.43   130.1  622.26   132.6   622.2   140.1  622.04   147.6  622.86
   150.1  623.14   160.1   624.7   170.1  625.78   180.1  626.57   190.1  627.28
   220.1  629.02   250.1  631.32   300.2  634.73   310.2   635.6   320.2  636.78
   340.2  640.09   350.2  641.59   360.2   642.9
#Mann= 3 , 0 , 0
       0     .06       0   132.6    .045       0   147.6     .06       0
Bank Sta=132.6,147.6
XS Rating Curve= 0 ,0
Exp/Cntr=0.3,0.1

Type RM Length L Ch R = 1 ,11595.3 ,286.6,285.8,285
XS GIS Cut Line= 2
     1556111.459       495563.73     1555972.334      495752.296
#Sta/Elev= 26
     9.8  628.23    19.5  628.14    29.3  628.09    39.1  628.08    48.8  628.07
    58.6   628.2    68.3  628.04    78.1  626.71    87.9  623.49    97.6   620.8
    99.9  620.62   107.4  620.03   114.9   620.5   117.2  620.65   126.9  622.83
   136.7  624.85   146.5  626.73   156.2  628.51     166  630.04   175.8  630.98
   185.5  631.61   195.3   632.1     205  632.62   214.8   633.5   224.6   635.9
   234.3  640.46
#Mann= 3 , 0 , 0
       0     .06       0    99.9    .045       0   114.9     .06       0
Bank Sta=99.9,114.9
XS Rating Curve= 0 ,0
Exp/Cntr=0.3,0.1

Type RM Length L Ch R = 1 ,11309.5 ,214.1,218.3,222.4
XS GIS Cut Line= 2
     1555971.184      495299.277     1555806.763      495536.134
#Sta/Elev= 25
     9.9  627.59    19.9  626.69    29.8  625.93    49.7  624.54    69.6  623.21
    89.5   622.1   109.4  621.28   119.3  621.06   139.2  620.91   149.1  620.39
   159.1  617.77     169  615.63   171.5  615.54     179  615.25   186.5  617.25
   188.9  617.88   198.9  623.19   208.8  626.22   218.7  627.05   228.7   627.6
   238.6  629.32   248.6     633   258.5  638.64   278.4  650.35   288.3  656.33
#Mann= 3 , 0 , 0
       0     .06       0   171.5    .045       0   186.5     .06       0
Bank Sta=171.5,186.5
XS Rating Curve= 0 ,0
Exp/Cntr=0.3,0.1

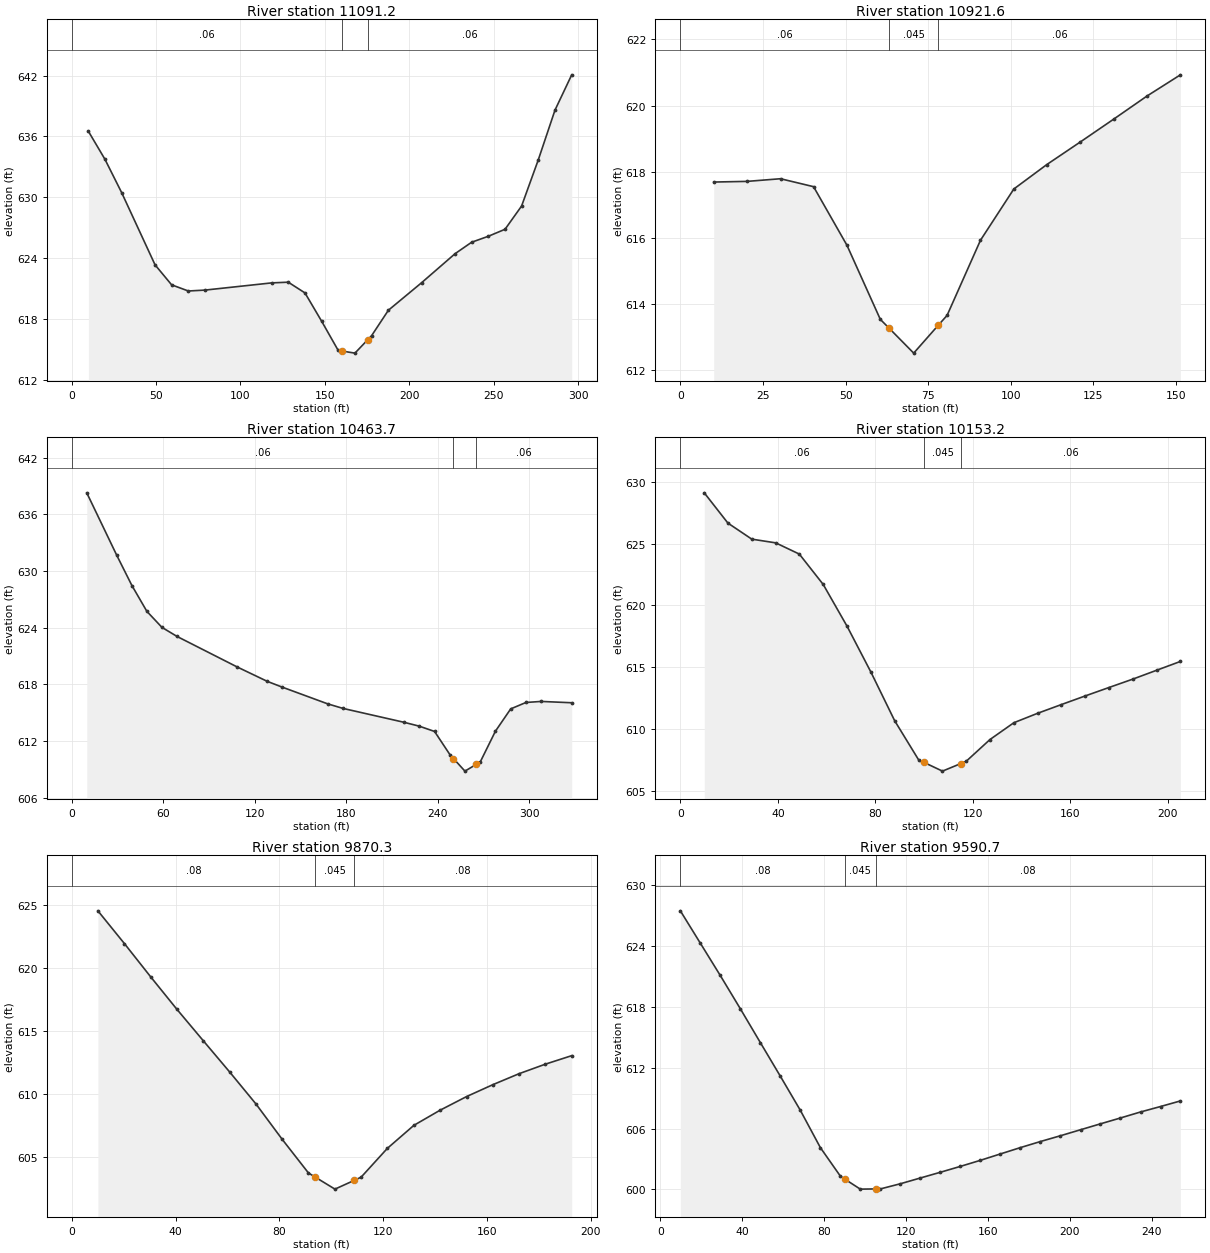
Type RM Length L Ch R = 1 ,11091.2 ,170.3,169.6,168.8
XS GIS Cut Line= 2
     1555838.717      495173.231     1555627.825      495381.152
#Sta/Elev= 26
     9.9  636.51    19.7  633.75    29.6  630.46    49.4  623.33    59.2  621.36
    69.1  620.75      79  620.84   118.5  621.55   128.3  621.62   138.2  620.56
   148.1  617.76   157.9  614.88   160.3  614.82   167.8  614.62   175.3  615.93
   177.7  616.35   187.6  618.85   207.3  621.57   227.1  624.43   236.9  625.56
   246.8  626.15   256.7  626.84   266.5  629.13   276.4  633.69   286.3   638.6
   296.2  642.08
#Mann= 3 , 0 , 0
       0     .06       0   160.3    .045       0   175.3     .06       0
Bank Sta=160.3,175.3
XS Rating Curve= 0 ,0
Exp/Cntr=0.3,0.1

Type RM Length L Ch R = 1 ,10921.6 ,477.5,458,438.4
XS GIS Cut Line= 2
     1555661.744      495108.555     1555557.784      495218.456
#Sta/Elev= 17
    10.1  617.69    20.2  617.71    30.3  617.79    40.3  617.55    50.4  615.78
    60.5  613.54    63.1  613.28    70.6  612.52    78.1  613.37    80.7  613.66
    90.8  615.93   100.9  617.48   110.9  618.22     121   618.9   131.1  619.59
   141.2  620.29   151.3  620.93
#Mann= 3 , 0 , 0
       0     .06       0    63.1    .045       0    78.1     .06       0
Bank Sta=63.1,78.1
XS Rating Curve= 0 ,0
Exp/Cntr=0.3,0.1

Type RM Length L Ch R = 1 ,10463.7 ,322.1,310.5,298.8
XS GIS Cut Line= 3
     1555370.655      494817.466     1555266.694      494936.278
     1555281.546      495105.585
#Sta/Elev= 24
     9.9  638.28    29.6  631.65    39.5  628.46    49.3  625.73    59.2  624.03
    69.1  623.07   108.5  619.84   128.3  618.31   138.1   617.7   167.9  615.93
   177.9  615.45   217.9  613.98   227.9  613.57   237.9  613.01   247.9  610.57
   250.3  610.14   257.8  608.81   265.3  609.53   267.8  609.77   277.8  613.04
   287.8   615.4   297.8  616.08   307.8  616.19   327.8  616.05
#Mann= 3 , 0 , 0
       0     .06       0   250.3    .045       0   265.3     .06       0
Bank Sta=250.3,265.3
XS Rating Curve= 0 ,0
Exp/Cntr=0.3,0.1

Type RM Length L Ch R = 1 ,10153.2 ,279.9,283,286
XS GIS Cut Line= 2
     1554978.575      495105.585     1555094.417      495274.892
#Sta/Elev= 23
     9.8  629.12    19.5  626.67    29.3  625.37    39.1  625.07    48.8  624.16
    58.6   621.7    68.4  618.31    78.2  614.59    87.9  610.67    97.7  607.51
     100  607.29   107.5  606.59     115   607.2   117.2  607.38     127  609.15
   136.8  610.51   146.5  611.27   156.3  611.98   166.1  612.68   175.8  613.36
   185.6  614.04   195.4  614.76   205.1  615.47
#Mann= 3 , 0 , 0
       0     .06       0     100    .045       0     115     .06       0
Bank Sta=100,115
XS Rating Curve= 0 ,0
Exp/Cntr=0.3,0.1

Type RM Length L Ch R = 1 ,9870.3  ,273.3,279.5,285.7
XS GIS Cut Line= 2
     1554752.832       495251.13     1554838.971      495423.407
#Sta/Elev= 21
    10.1   624.5    20.3  621.91    30.4  619.28    40.5  616.71    50.7  614.21
    60.8  611.75      71   609.2    81.1   606.4    91.2  603.74    93.9   603.4
   101.4  602.46   108.9  603.16   111.5  603.41   121.6  605.69   131.8  607.51
   141.9  608.71   152.1  609.79   162.2  610.73   172.3   611.6   182.5  612.36
   192.6  613.03
#Mann= 3 , 0 , 0
       0     .08       0    93.9    .045       0   108.9     .08       0
Bank Sta=93.9,108.9
XS Rating Curve= 0 ,0
Exp/Cntr=0.3,0.1

Type RM Length L Ch R = 1 ,9590.7  ,162.8,179,195
XS GIS Cut Line= 2
     1554504.045       495282.03     1554552.336      495531.535
#Sta/Elev= 28
     9.8  627.45    19.5  624.28    29.3  621.08    39.1   617.8    48.9  614.46
    58.6  611.17    68.4   607.8    78.2  604.12      88   601.3    90.2  601.01
    97.7  600.03   105.2  600.05   107.5  600.05   117.3  600.56   127.1  601.13
   136.8  601.69   146.6  602.27   156.4  602.87   166.2   603.5   175.9  604.12
   185.7  604.72   195.5  605.29   205.3  605.88     215  606.46   224.8  607.04
   234.6  607.63   244.4  608.17   254.1  608.72
#Mann= 3 , 0 , 0
     9.8     .08       0    90.2    .045       0   105.2     .08       0
Bank Sta=90.2,105.2
XS Rating Curve= 0 ,0
Exp/Cntr=0.3,0.1

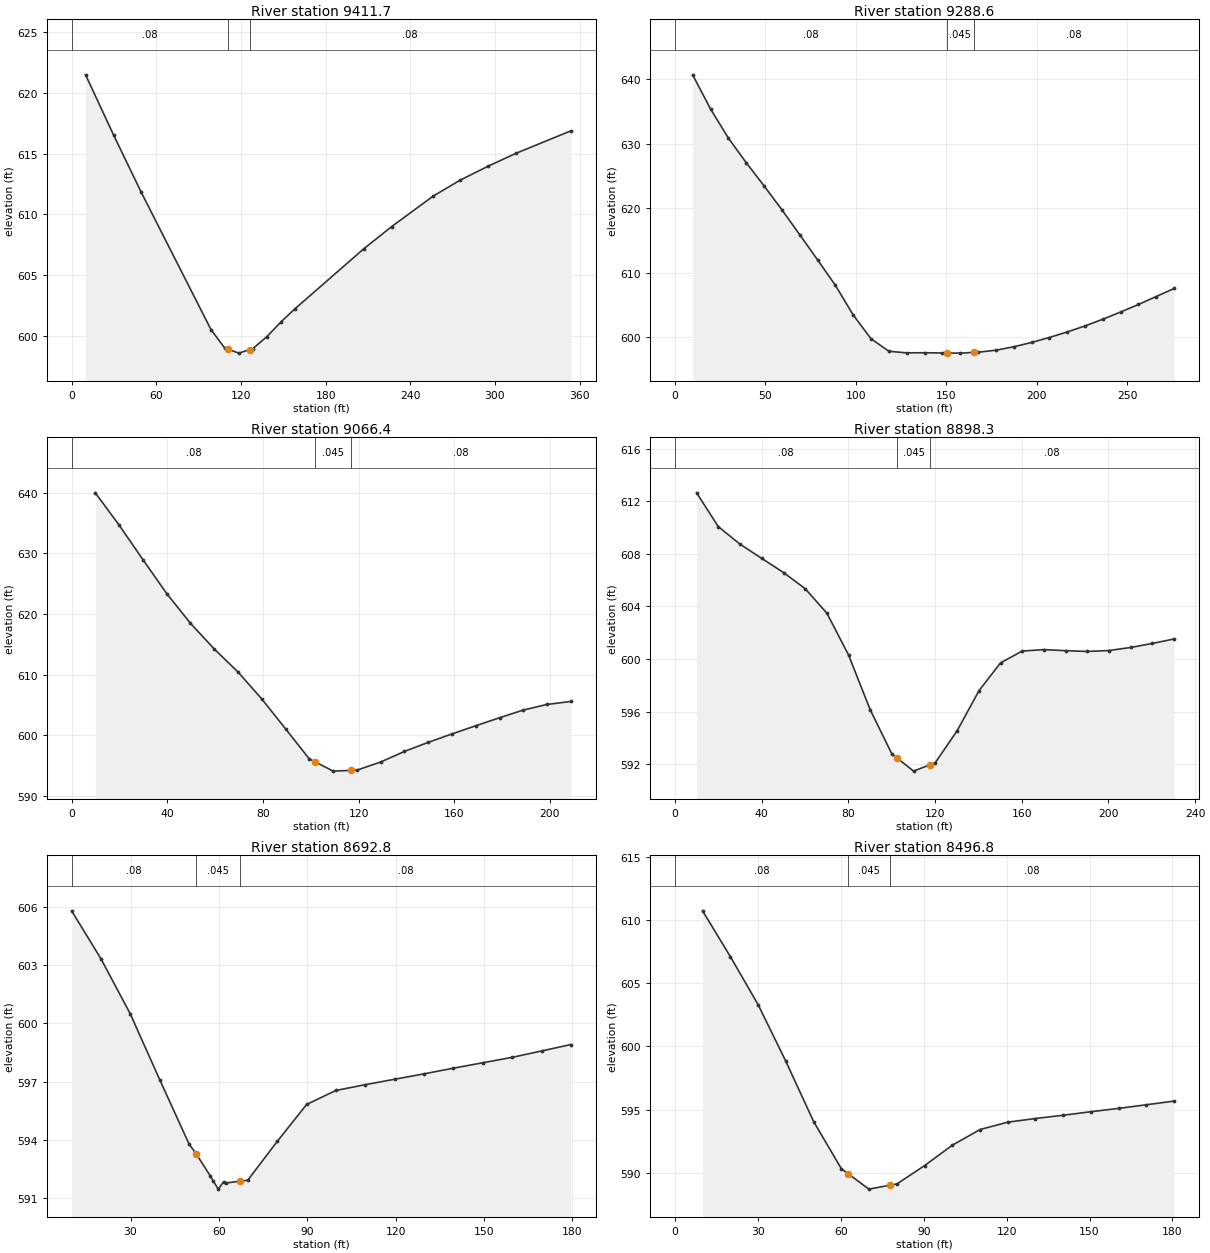
Type RM Length L Ch R = 1 ,9411.7  ,118.4,123.1,128
XS GIS Cut Line= 3
     1554405.307      495304.595     1554320.271      495460.877
     1554259.138      495625.818
#Sta/Elev= 19
     9.9  621.49    29.7  616.55    49.4  611.81    98.8  600.52   108.7  598.98
   111.1  598.89   118.6  598.59   126.1  598.88   128.5  598.97   138.4  599.95
   148.3  601.15   158.2  602.23   207.2  607.19   226.8     609   256.1   611.5
   275.6  612.84   295.2  613.97   314.7  615.02   353.8  616.88
#Mann= 3 , 0 , 0
       0     .08       0   111.1    .045       0   126.1     .08       0
Bank Sta=111.1,126.1
XS Rating Curve= 0 ,0
Exp/Cntr=0.3,0.1

Type RM Length L Ch R = 1 ,9288.6  ,218.6,222.2,225.8
XS GIS Cut Line= 2
      1554347.53      495233.116     1554166.342      495441.037
#Sta/Elev= 30
     9.8   640.7    19.7  635.39    29.5  630.91    39.4  627.08    49.2  623.51
    59.1  619.79    68.9  615.94    78.8  612.03    88.6   608.1    98.5  603.48
   108.3  599.81   118.2  597.86     128  597.61   137.9  597.63   147.7   597.6
   150.1  597.59   157.6  597.57   165.1  597.68   167.4  597.71   177.3  598.02
   187.1  598.55     197  599.22   206.8  599.99   216.7  600.85   226.5  601.78
   236.4  602.82   246.2  603.94   256.1  605.11   265.9  606.34   275.8  607.59
#Mann= 3 , 0 , 0
       0     .08       0   150.1    .045       0   165.1     .08       0
Bank Sta=150.1,165.1
XS Rating Curve= 0 ,0
Exp/Cntr=0.3,0.1

Type RM Length L Ch R = 1 ,9066.4  ,163.8,168.1,172.6
XS GIS Cut Line= 2
     1554218.178      495093.704     1554057.782      495227.367
#Sta/Elev= 23
     9.9  639.97    19.9  634.63    29.8  628.96    39.8  623.34    49.7  618.45
    59.7  614.19    69.6  610.41    79.5  605.98    89.5  601.03    99.4  596.08
   101.9  595.58   109.4  594.06   116.9  594.18   119.3  594.22   129.3  595.57
   139.2  597.31   149.1   598.8   159.1   600.2     169  601.54     179  602.87
   188.9  604.13   198.8  605.06   208.8  605.55
#Mann= 3 , 0 , 0
       0     .08       0   101.9    .045       0   116.9     .08       0
Bank Sta=101.9,116.9
XS Rating Curve= 0 ,0
Exp/Cntr=0.3,0.1

Type RM Length L Ch R = 1 ,8898.3  ,209.7,205.5,199.7
XS GIS Cut Line= 2
     1554129.069      494974.892     1553930.059      495090.733
#Sta/Elev= 25
      10  612.63      20  610.06      30  608.73      40  607.65    50.1  606.57
    60.1  605.34    70.1  603.48    80.1   600.3    90.1  596.13   100.1  592.77
   102.6  592.45   110.1  591.47   117.6  591.95   120.1  592.11   130.2  594.54
   140.2  597.57   150.2   599.7   160.2   600.6   170.2  600.71   180.2  600.63
   190.2  600.57   200.2  600.64   210.2  600.87   220.3  601.18   230.3  601.52
#Mann= 3 , 0 , 0
       0     .08       0   102.6    .045       0   117.6     .08       0
Bank Sta=102.6,117.6
XS Rating Curve= 0 ,0
Exp/Cntr=0.3,0.1

Type RM Length L Ch R = 1 ,8692.8  ,201.8,196,190.3
XS GIS Cut Line= 2
     1554010.257      494826.377     1553870.653      494939.248
#Sta/Elev= 24
      10  605.81    19.9  603.35    29.9   600.5    39.9   597.1    49.9  593.77
    52.3  593.27   57.08  592.13   57.99  591.89    59.8  591.45   61.61  591.83
   62.52  591.77    67.3  591.86    69.8  591.91    79.8  593.91    89.8  595.82
    99.7  596.54   109.7  596.84   119.7  597.12   129.7   597.4   139.6  597.69
   149.6  597.97   159.6  598.25   169.6  598.58   179.5  598.91
#Mann= 3 , 0 , 0
      10     .08       0    52.3    .045       0    67.3     .08       0
Bank Sta=52.3,67.3
XS Rating Curve= 0 ,0
Exp/Cntr=0.3,0.1

Type RM Length L Ch R = 1 ,8496.8  ,180.4,175.8,171.2
XS GIS Cut Line= 2
     1553852.831      494695.684       1553745.9      494841.228
#Sta/Elev= 20
      10  610.73    20.1  607.09    30.1   603.3    40.1  598.83    50.2  594.04
    60.2  590.32    62.7  589.91    70.2   588.7    77.7  589.01    80.3  589.11
    90.3  590.56   100.3  592.17   110.4  593.42   120.4     594   130.4  594.29
   140.5  594.55   150.5  594.83   160.5  595.09   170.6  595.38   180.6  595.67
#Mann= 3 , 0 , 0
       0     .08       0    62.7    .045       0    77.7     .08       0
Bank Sta=62.7,77.7
XS Rating Curve= 0 ,0
Exp/Cntr=0.3,0.1

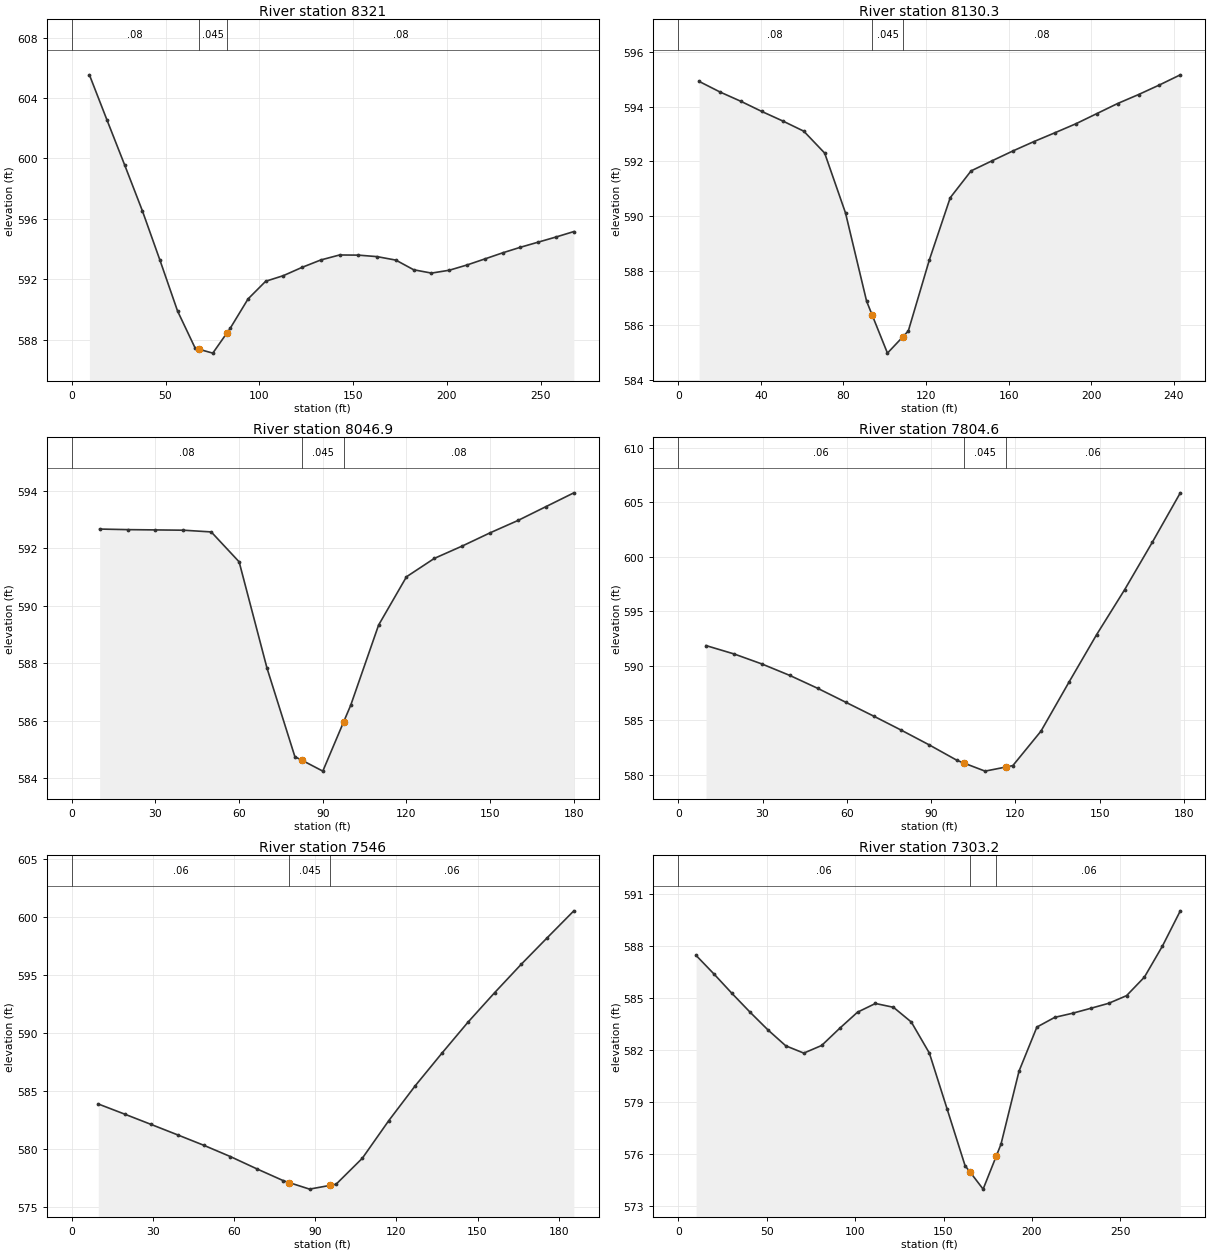
Type RM Length L Ch R = 1 ,8321    ,199.5,190.7,181.9
XS GIS Cut Line= 4
     1553684.386      494612.132     1553635.949      494714.031
     1553684.241      494749.674     1553707.237      494841.658
#Sta/Elev= 30
     9.4  605.54    18.8  602.54    28.2  599.57    37.6  596.55      47  593.27
    56.4   589.9    65.8  587.44    67.7  587.37    75.2  587.11    82.7  588.44
    84.6  588.78      94   590.7   103.4  591.87   112.8  592.24   122.8  592.79
   132.8  593.28   142.8  593.61   152.8   593.6   162.8   593.5   172.8  593.27
   182.3  592.63   191.8  592.41   201.3   592.6   210.8  592.95   220.3  593.35
   229.7  593.75   239.2  594.12   248.7  594.46   258.2   594.8   267.7  595.16
#Mann= 3 , 0 , 0
       0     .08       0    67.7    .045       0    82.7     .08       0
Bank Sta=67.7,82.7
XS Rating Curve= 0 ,0
Exp/Cntr=0.3,0.1

Type RM Length L Ch R = 1 ,8130.3  ,89.5,83.4,77.4
XS GIS Cut Line= 2
     1553475.434      494552.899      1553462.33      494795.666
#Sta/Elev= 26
    10.1  594.92    20.3  594.53    30.4  594.19    40.5  593.82    50.7  593.47
    60.8   593.1    70.9   592.3      81  590.11    91.2  586.89    93.8   586.4
   101.3  584.99   108.8  585.59   111.4   585.8   121.6   588.4   131.7  590.67
   141.8  591.65     152  592.02   162.1  592.38   172.2  592.72   182.3  593.04
   192.5  593.37   202.6  593.74   212.7  594.11   222.9  594.44     233  594.79
   243.1  595.16
#Mann= 3 , 0 , 0
       0     .08       0    93.8    .045       0   108.8     .08       0
Bank Sta=93.8,108.8
XS Rating Curve= 0 ,0
Exp/Cntr=0.3,0.1

Type RM Length L Ch R = 1 ,8046.9  ,229,242.3,255.6
XS GIS Cut Line= 2
     1553368.047      494570.306      1553405.99      494746.225
#Sta/Elev= 20
      10  592.67      20  592.65      30  592.64      40  592.63      50  592.57
      60  591.53      70  587.83      80  584.75    82.5  584.63      90  584.25
    97.5  585.97     100  586.54     110  589.33     120  591.01     130  591.65
     140  592.08     150  592.54     160  592.97     170  593.45     180  593.93
#Mann= 3 , 0 , 0
       0     .08       0    82.5    .045       0    97.5     .08       0
Bank Sta=82.5,97.5
XS Rating Curve= 0 ,0
Exp/Cntr=0.3,0.1

Type RM Length L Ch R = 1 ,7804.6  ,251.3,258.6,265.8
XS GIS Cut Line= 2
     1553202.335      494597.664     1553136.989         494764.
#Sta/Elev= 20
     9.9  591.85    19.9  591.08    29.8  590.16    39.7  589.11    49.6  587.93
    59.6  586.65    69.5  585.38    79.4  584.08    89.4  582.72    99.3   581.3
   101.7  581.06   109.2  580.32   116.7   580.7   119.1  580.83   129.1  583.99
     139  588.46   148.9  592.85   158.9  596.99   168.8  601.37   178.7  605.88
#Mann= 3 , 0 , 0
       0     .06       0   101.7    .045       0   116.7     .06       0
Bank Sta=101.7,116.7
XS Rating Curve= 0 ,0
Exp/Cntr=0.3,0.1

Type RM Length L Ch R = 1 ,7546    ,239.6,242.8,246
XS GIS Cut Line= 2
     1553006.295      494490.733     1552887.483      494633.307
#Sta/Elev= 21
     9.8  583.88    19.5  583.01    29.3  582.12    39.1  581.22    48.8  580.32
    58.6  579.35    68.4  578.29    78.1  577.28    80.4   577.1    87.9  576.54
    95.4  576.86    97.7  576.96   107.4   579.2   117.2  582.45     127  585.46
   136.8  588.25   146.5  590.94   156.3  593.47   166.1  595.91   175.8  598.22
   185.6  600.53
#Mann= 3 , 0 , 0
       0     .06       0    80.4    .045       0    95.4     .06       0
Bank Sta=80.4,95.4
XS Rating Curve= 0 ,0
Exp/Cntr=0.3,0.1

Type RM Length L Ch R = 1 ,7303.2  ,167.5,182.8,198.1
XS GIS Cut Line= 2
     1552875.602      494309.544     1552664.711      494499.644
#Sta/Elev= 30
    10.1  587.46    20.3  586.38    30.4  585.27    40.6  584.19    50.7  583.17
    60.8  582.25      71  581.83    81.1  582.27    91.3  583.26   101.4  584.19
   111.5  584.69   121.7  584.47   131.8  583.62     142  581.83   152.1  578.59
   162.2  575.34   164.9  574.99   172.4  573.99   179.9  575.91   182.5  576.58
   192.7  580.79   202.8  583.33   212.9  583.89   223.1  584.13   233.2  584.41
   243.4   584.7   253.5  585.14   263.6  586.21   273.8     588   283.9  590.03
#Mann= 3 , 0 , 0
       0     .06       0   164.9    .045       0   179.9     .06       0
Bank Sta=164.9,179.9
XS Rating Curve= 0 ,0
Exp/Cntr=0.3,0.1