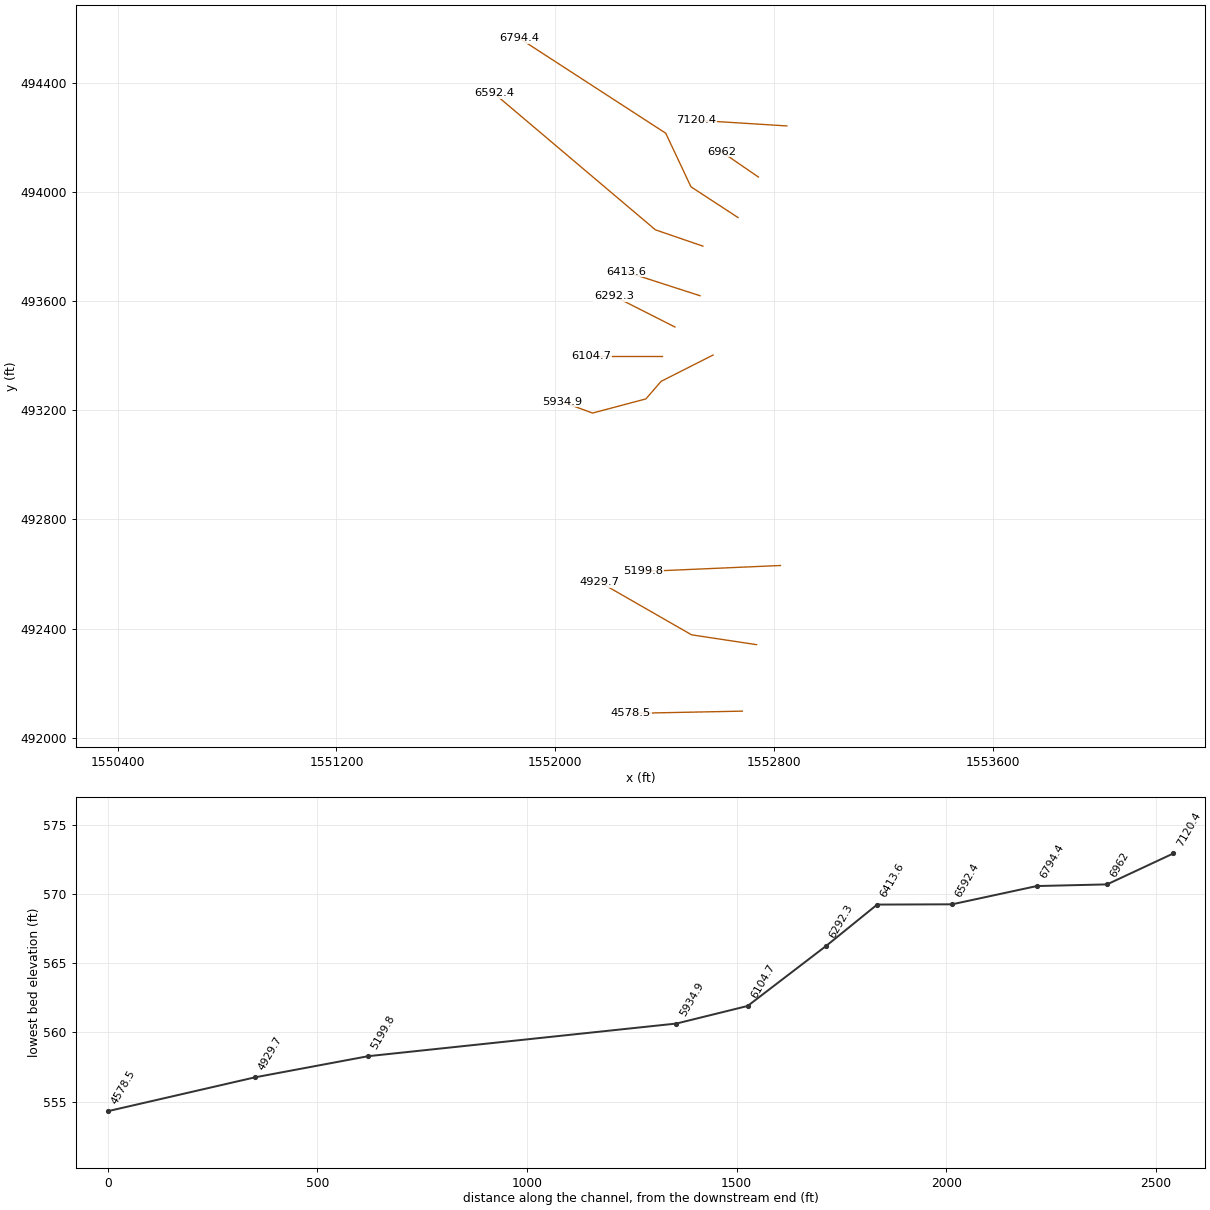
HEC-RAS study NRTHCMPCR.prj: NRTHCMPCR

--- NRTHCMPCR.g01 (geometry) --- (continued)

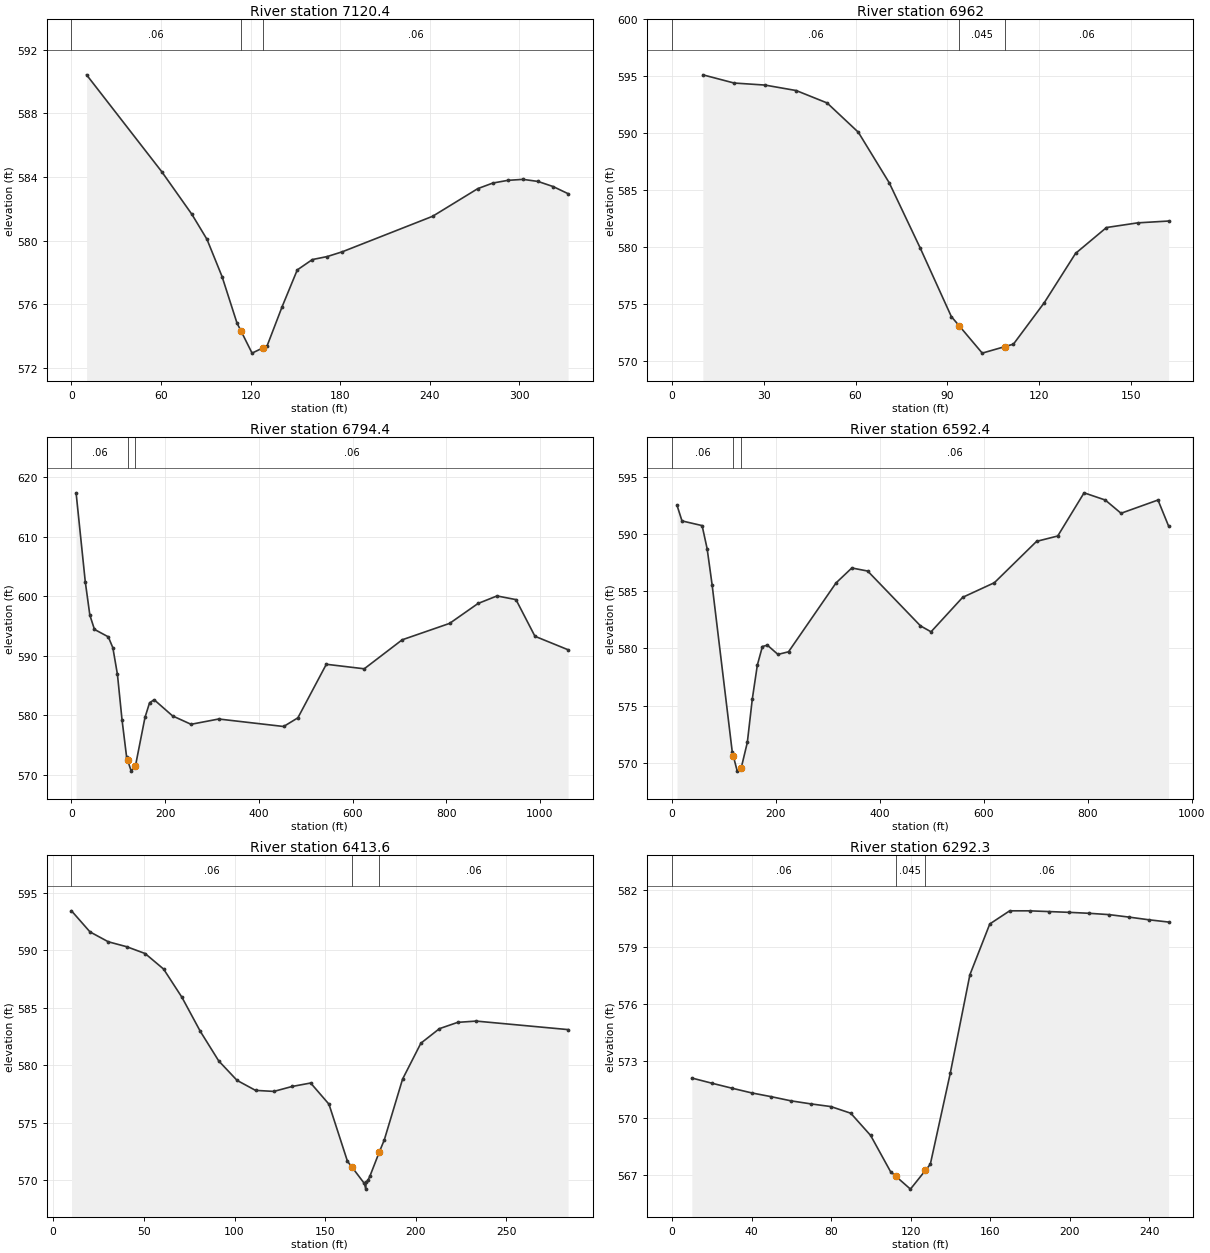
Type RM Length L Ch R = 1 ,7120.4  ,170.6,158.3,146.1
XS GIS Cut Line= 2
     1552845.899      494241.227     1552513.749      494262.161
#Sta/Elev= 23
    10.1  590.43    60.5  584.34    80.7  581.66    90.8  580.09   100.9  577.75
   110.9  574.83   113.5  574.35     121  572.94   128.5  573.28   131.1   573.4
   141.2  575.87   151.3  578.17   161.4  578.82   171.4  579.01   181.5  579.31
     242  581.54   272.3  583.28   282.4  583.63   292.5   583.8   302.6  583.86
   312.6  583.73   322.7  583.41   332.8  582.96
#Mann= 3 , 0 , 0
       0     .06       0   113.5    .045       0   128.5     .06       0
Bank Sta=113.5,128.5
XS Rating Curve= 0 ,0
Exp/Cntr=0.3,0.1

Type RM Length L Ch R = 1 ,6962    ,167.1,167.6,168.1
XS GIS Cut Line= 2
     1552741.939      494054.098     1552608.275      494146.178
#Sta/Elev= 18
    10.1  595.14    20.3  594.42    30.4  594.24    40.6  593.76    50.7  592.67
    60.9   590.1      71  585.66    81.2  579.89    91.3  573.91    93.9  573.09
   101.4   570.7   108.9  571.28   111.6  571.49   121.7  575.14   131.9  579.46
     142  581.73   152.2  582.14   162.3   582.3
#Mann= 3 , 0 , 0
       0     .06       0    93.9    .045       0   108.9     .06       0
Bank Sta=93.9,108.9
XS Rating Curve= 0 ,0
Exp/Cntr=0.3,0.1

Type RM Length L Ch R = 1 ,6794.4  ,195.5,201.9,208.4
XS GIS Cut Line= 4
     1552667.681      493905.583     1552495.404      494018.455
     1552403.324      494214.495      1551868.67       494562.02
#Sta/Elev= 30
     9.8  617.41    29.4  602.45    39.2  596.82      49  594.43    78.5  593.18
    88.3  591.34    98.1  586.84   107.9   579.2   117.7  572.92     120  572.37
   127.5  570.58     135  571.49   137.3  571.77   156.9  579.62   166.7  582.09
   176.5  582.59   215.8  579.87   255.2  578.46   314.3  579.35   452.9  578.09
   483.3  579.55     544  588.56     625   587.8     706  592.68   807.2  595.44
   867.9  598.79   908.4  600.06   948.9  599.44   989.4  593.27  1060.2     591
#Mann= 3 , 0 , 0
       0     .06       0     120    .045       0     135     .06       0
Bank Sta=120,135
XS Rating Curve= 0 ,0
Exp/Cntr=0.3,0.1

Type RM Length L Ch R = 1 ,6592.4  ,178.4,178.8,179.2
XS GIS Cut Line= 3
     1552539.044      493801.093     1552365.425      493860.882
     1551776.591      494360.039
#Sta/Elev= 30
     9.7  592.54    19.3  591.17      58  590.76    67.7  588.73    77.3  585.56
     116  570.94   118.1  570.57   125.6  569.26   133.1  569.51     145  571.77
   154.6  575.58   164.3  578.55     174  580.17   183.6  580.29   203.9  579.48
   224.3  579.71   315.7  585.74   346.1  587.05   376.6  586.78   478.2  581.98
   498.5  581.46   559.4  584.48   620.4  585.76   701.6  589.38   742.3  589.85
     793  593.63   833.7     593   864.1  591.84   935.2     593   955.6  590.72
#Mann= 3 , 0 , 0
       0     .06       0   118.1    .045       0   133.1     .06       0
Bank Sta=118.1,133.1
XS Rating Curve= 0 ,0
Exp/Cntr=0.3,0.1

Type RM Length L Ch R = 1 ,6413.6  ,124.9,121.3,117.7
XS GIS Cut Line= 2
     1552528.696      493619.425     1552258.494       493706.81
#Sta/Elev= 30
    10.1  593.42    20.3  591.59    30.4  590.73    40.6   590.3    50.7  589.71
    60.9  588.36      71  585.91    81.1  582.96    91.3  580.38   101.4  578.69
   111.6  577.82   121.7  577.73   131.8  578.16     142  578.46   152.1  576.62
   162.3  571.66   164.9  571.13  171.62  569.73   172.4  569.24  172.58  569.83
   173.6  570.01  174.74  570.39   179.9  572.48   182.6  573.51   192.7   578.8
   202.8  581.92     213  583.18   223.1  583.73   233.3  583.84     284   583.1
#Mann= 3 , 0 , 0
    10.1     .06       0   164.9    .045       0   179.9     .06       0
Bank Sta=164.9,179.9
XS Rating Curve= 0 ,0
Exp/Cntr=0.3,0.1

Type RM Length L Ch R = 1 ,6292.3  ,176.6,187.6,198.5
XS GIS Cut Line= 2
     1552437.148       493504.88     1552214.375      493617.752
#Sta/Elev= 27
      10   572.1      20  571.83      30  571.57      40  571.32    49.9  571.12
    59.9   570.9    69.9  570.74    79.9   570.6    89.9  570.25    99.9  569.08
   109.9  567.18   112.4  566.95   119.9  566.26   127.4  567.24   129.9  567.57
   139.9  572.34   149.8  577.53   159.8   580.2   169.8  580.89   179.8  580.89
   189.8  580.85   199.8  580.81   209.8  580.76   219.8  580.69   229.8  580.56
   239.7  580.42   249.7   580.3
#Mann= 3 , 0 , 0
       0     .06       0   112.4    .045       0   127.4     .06       0
Bank Sta=112.4,127.4
XS Rating Curve= 0 ,0
Exp/Cntr=0.3,0.1

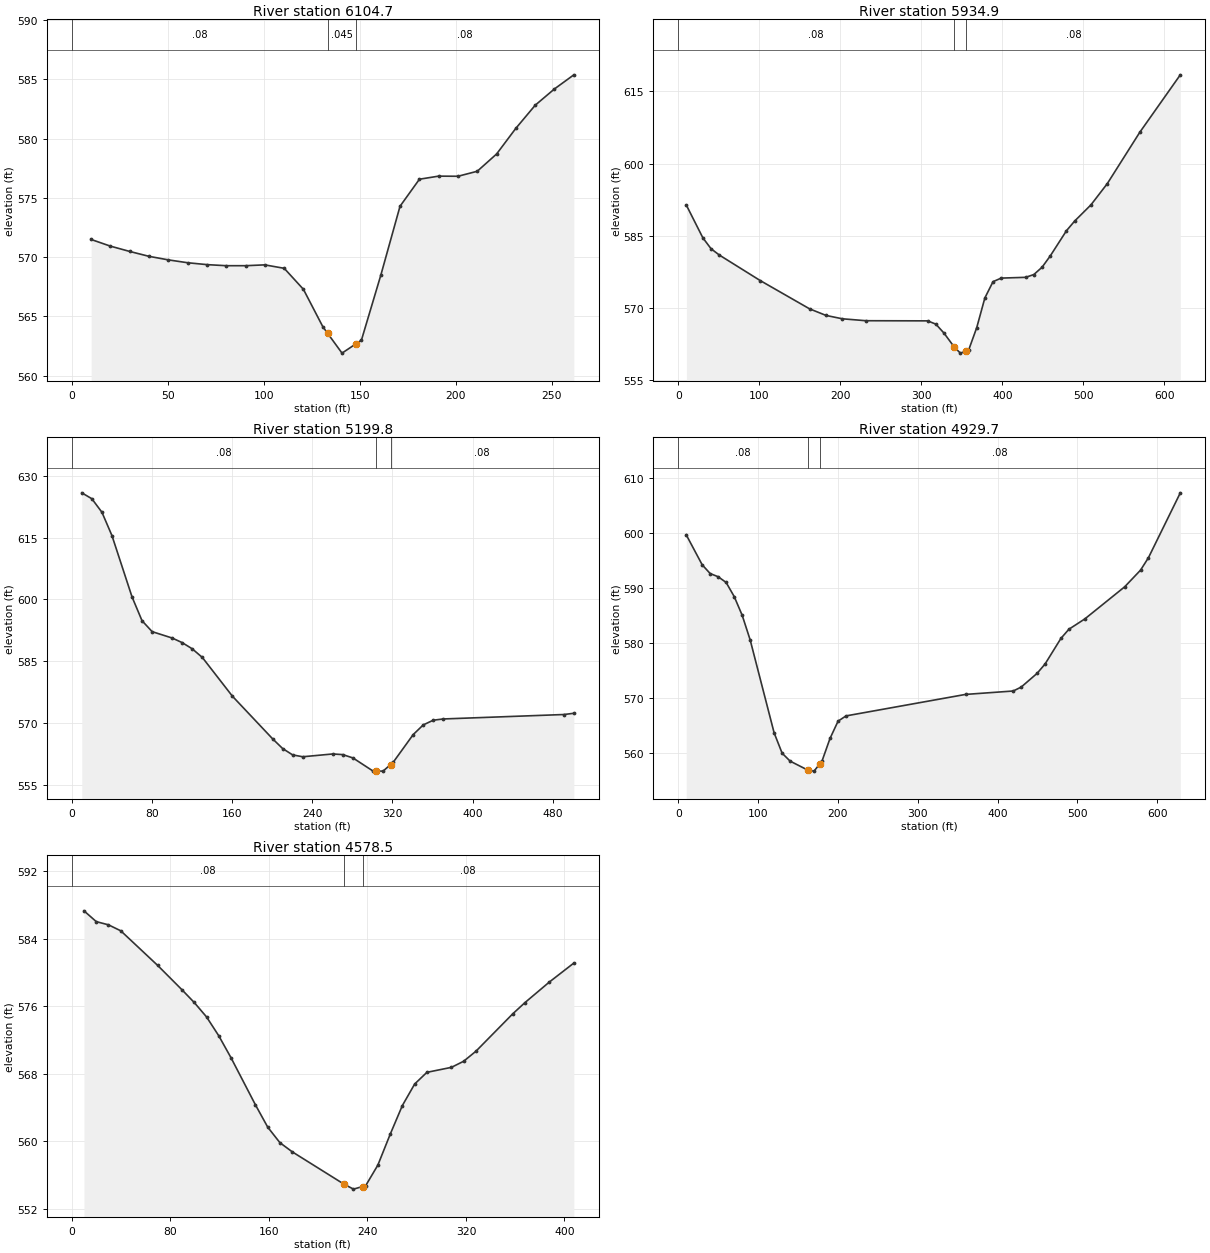
Type RM Length L Ch R = 1 ,6104.7  ,163.9,169.8,175.8
XS GIS Cut Line= 2
     1552391.443      493397.662     1552130.057      493397.662
#Sta/Elev= 28
    10.1  571.49    20.1  570.93    30.2  570.48    40.2  570.07    50.3  569.77
    60.3  569.53    70.4  569.37    80.4  569.28    90.5  569.28   100.5  569.35
   110.6  569.06   120.6  567.29   130.7  564.14   133.2  563.58   140.7  561.91
   148.2  562.72   150.8     563   160.9  568.48   170.9  574.29     181  576.57
     191  576.83   201.1  576.82   211.1  577.24   221.2   578.7   231.2  580.86
   241.3  582.81   251.3  584.18   261.4  585.37
#Mann= 3 , 0 , 0
       0     .08       0   133.2    .045       0   148.2     .08       0
Bank Sta=133.2,148.2
XS Rating Curve= 0 ,0
Exp/Cntr=0.3,0.1

Type RM Length L Ch R = 1 ,5934.9  ,741.3,735.1,728.4
XS GIS Cut Line= 5
     1552576.269      493402.258     1552386.553      493305.962
     1552330.801      493241.595     1552135.997      493189.741
     1552023.126      493231.325
#Sta/Elev= 30
    10.1  591.35    30.4  584.58    40.5  582.32    50.7  581.01   101.3   575.7
   162.1  569.84   182.4  568.47   202.6  567.77   231.7  567.37     308  567.34
   318.1  566.65   328.1  564.79   340.8  561.89   348.3  560.64   355.8  561.08
   358.4  561.23   368.5  565.94   378.5  572.09   388.6  575.48   398.7  576.22
   428.9  576.38     439  576.96   449.1  578.47   459.2  580.81   479.3  586.07
   489.4  588.07   509.5  591.43   529.6  595.82   569.7  606.48   619.8  618.43
#Mann= 3 , 0 , 0
       0     .08       0   340.8    .045       0   355.8     .08       0
Bank Sta=340.8,355.8
XS Rating Curve= 0 ,0
Exp/Cntr=0.3,0.1

Type RM Length L Ch R = 1 ,5199.8  ,274.5,270.1,266.1
XS GIS Cut Line= 2
     1552822.696      492631.499     1552322.172      492609.618
#Sta/Elev= 30
      10  625.88      20  624.45    30.1  621.16    40.1  615.49    60.1  600.62
    70.1  594.82    80.2  592.16   100.2  590.61   110.2  589.49   120.2  587.99
   130.3  585.89   160.3  576.48   200.4  566.13   210.4  563.77   220.4  562.22
   230.5  561.77   260.5  562.45   270.5  562.29   280.6  561.48   300.6   558.3
   303.1  558.29   310.6  558.28   318.1  559.86   320.6  560.38   340.7  567.16
   350.7   569.5   360.7  570.65   370.7  570.95     491  572.03     501  572.33
#Mann= 3 , 0 , 0
       0     .08       0   303.1    .045       0   318.1     .08       0
Bank Sta=303.1,318.1
XS Rating Curve= 0 ,0
Exp/Cntr=0.3,0.1

Type RM Length L Ch R = 1 ,4929.7  ,347,351.2,355.3
XS GIS Cut Line= 3
     1552735.173      492341.578     1552497.708      492377.622
     1552160.801      492571.327
#Sta/Elev= 30
      10  599.67      30  594.22      40  592.63      50  592.05      60  591.01
    70.1  588.45    80.1  585.05    90.1  580.57   120.1   563.7   130.1  560.01
   140.1  558.57   162.6  556.91   170.1  556.75   177.6  558.13   180.1  558.59
   190.1  562.69   200.2  565.83   210.2  566.78   359.8  570.68   419.5   571.3
   429.5  572.01   449.4   574.5   459.4   576.2   479.3  580.86   489.3  582.52
   509.2  584.39   559.1  590.22     579  593.25   588.9  595.51   628.8  607.29
#Mann= 3 , 0 , 0
       0     .08       0   162.6    .045       0   177.6     .08       0
Bank Sta=162.6,177.6
XS Rating Curve= 0 ,0
Exp/Cntr=0.3,0.1

Type RM Length L Ch R = 1 ,4578.5  ,4622.2,4578.5,4534.7
XS GIS Cut Line= 2
     1552683.206      492098.154     1552275.675      492089.949
#Sta/Elev= 30
     9.9  587.28    19.9     586    29.8  585.62    39.8  584.91    69.6  580.83
    89.5  577.92    99.4  576.42   109.4  574.71   119.3  572.48   129.2  569.89
   149.1  564.29   159.1  561.64     169   559.8     179  558.72   221.2  554.87
   228.7   554.3   236.2  554.61   238.6  554.71   248.5  557.15   258.5   560.8
   268.4  564.21   278.4  566.76   288.3  568.14   308.2  568.73   318.1  569.45
   328.1  570.64   357.9  575.06   367.8  576.39   387.7  578.84   407.6  581.09
#Mann= 3 , 0 , 0
       0     .08       0   221.2    .045       0   236.2     .08       0
Bank Sta=221.2,236.2
XS Rating Curve= 0 ,0
Exp/Cntr=0.3,0.1

Chan Stop Cuts=-1
Use User Specified Reach Order=0